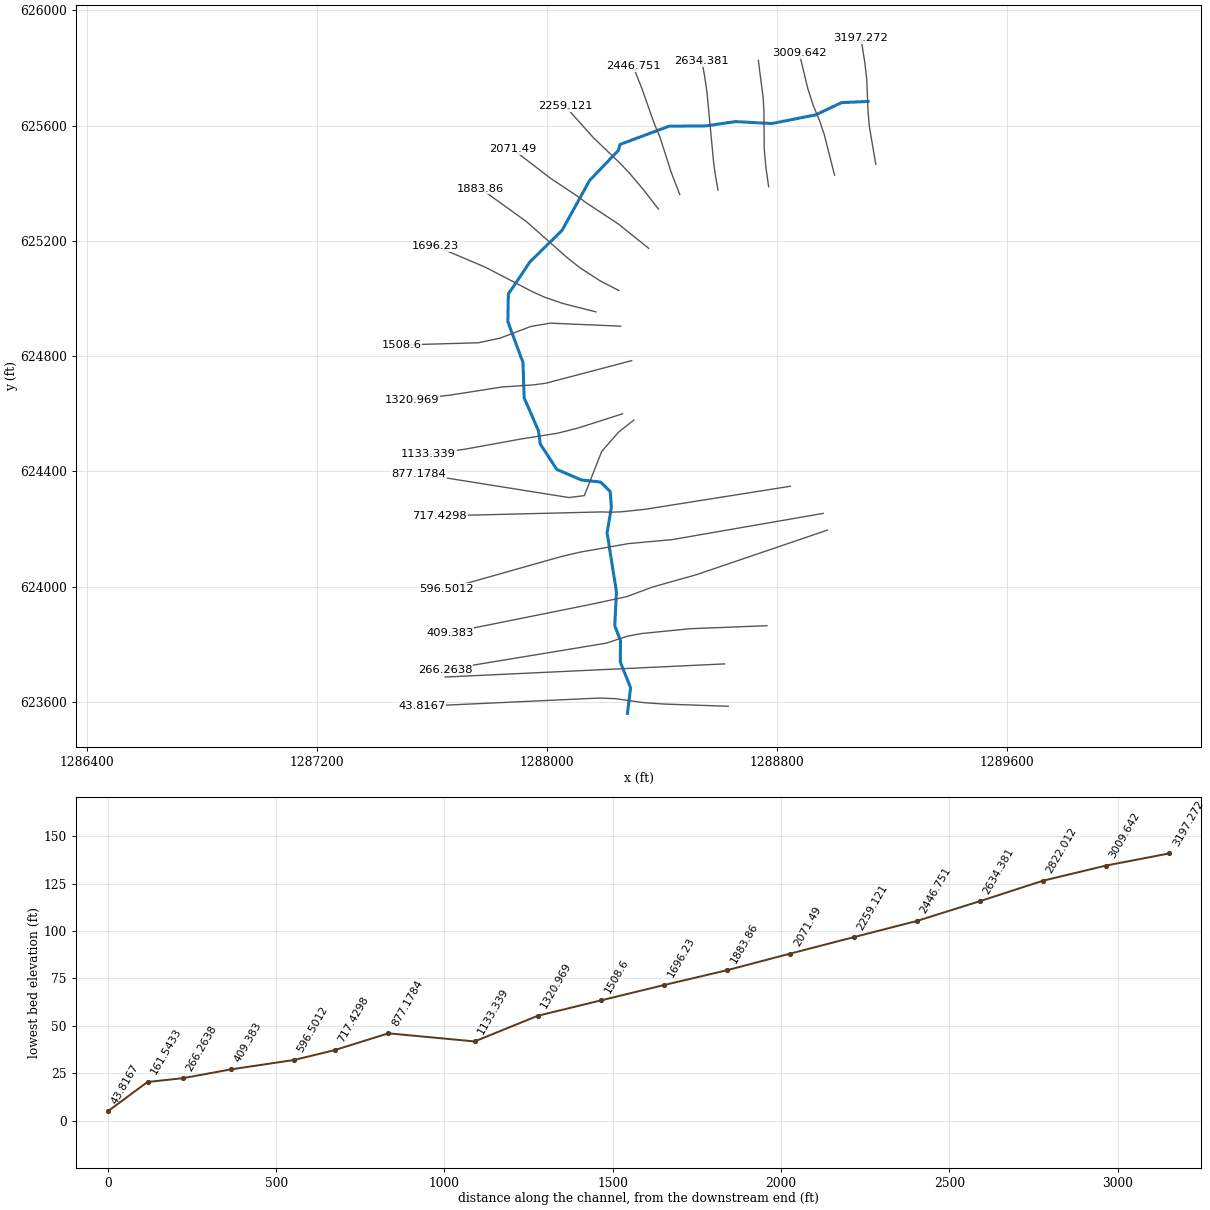
--- 707_ras.prj (project) ---

Proj Title=707
Current Plan=p01
Default Exp/Contr=0.3,0.1
English Units
Geom File=g01
Flow File=f01
Plan File=p01
Y Axis Title=Elevation
X Axis Title(PF)=Main Channel Distance
X Axis Title(XS)=Station
BEGIN DESCRIPTION:
RFD model 707 exported to HEC-RAS
END DESCRIPTION:

--- 707_ras.p01 (plan) ---

Plan Title=Plan 01
Program Version=4.10
Short Identifier=Plan 01
Geom File=g01
Flow File=f01
Subcritical Flow
Calc Critical at every XS
Secant Critical Depth

--- 707_ras.f01 (steady flow) ---

Flow Title=Flow 01
Program Version=5.01
Number of Profiles= 5
Profile Names=10yr,25yr,50yr,100yr,500yr
River Rch & RM=707,19,3197.272
  398.96  478.61  571.32  612.87  723.95
River Rch & RM=707,19,2634.381
  407.97  491.02  586.57  631.31   748.9
River Rch & RM=707,19,2446.751
  425.88  515.81  617.06  668.37  799.35
River Rch & RM=707,19,2259.121
  434.06  527.18  631.05  685.45  822.74
River Rch & RM=707,19, 2071.49
  513.96  639.83  770.21  857.78 1063.12
River Rch & RM=707,19, 1883.86
  525.63   656.5  790.87  883.71 1099.94
River Rch & RM=707,19, 1696.23
  530.51  663.49  799.54  894.62 1115.47
River Rch & RM=707,19,  1508.6
  661.77  854.84  1037.7  1199.7 1559.95
River Rch & RM=707,19,1320.969
  663.68  857.67 1041.24 1204.31  1566.8
River Rch & RM=707,19,1133.339
  672.75  871.12 1058.05 1226.21  1599.4
River Rch & RM=707,19,877.1784
  676.11   876.1 1064.27 1234.33 1611.51
River Rch & RM=707,19,717.4298
  680.91  883.24 1073.19 1245.97  1628.9
River Rch & RM=707,19,596.5012
  684.56  888.68 1079.99 1254.86 1642.19
River Rch & RM=707,19, 409.383
  686.02  890.84  1082.7  1258.4 1647.48
River Rch & RM=707,19,266.2638
  754.09  992.87 1210.49 1426.77 1901.73
River Rch & RM=707,19,161.5433
  756.91  997.12 1215.83 1433.85 1912.52
River Rch & RM=707,19, 43.8167
  766.49 1011.61 1234.01    1458 1949.39
Boundary for River Rch & Prof#=707,19,1
Up Type= 0
Dn Type= 2
Boundary for River Rch & Prof#=707,19,2
Up Type= 0
Dn Type= 2
Boundary for River Rch & Prof#=707,19,2
Up Type= 0
Dn Type= 2
Boundary for River Rch & Prof#=707,19,2
Up Type= 0
Dn Type= 2
Boundary for River Rch & Prof#=707,19,2
Up Type= 0
Dn Type= 2

--- 707_ras.g01 (geometry) ---

Geom Title=707
Program Version=4.10

River Reach=707,19
Reach XY= 30
1289116.41467343625683.9896909971289024.03132483625679.773425627
1288934.03135015625637.2734408811288781.53139425 625607.27345428
1288655.69809826625613.9401226611288551.53146191625598.940130178
1288424.86483262625598.106800844 1288254.0315478625534.773491323
1288248.19821559625513.9401643371288148.19824199625409.773531542
1288052.36493189625236.4402525021287941.53162806625128.106954557
 1287865.6983138625015.6069902261287864.03164479624919.773685362
 1287916.5316251624778.1070592471287920.69828695624655.607095467
1287970.69826879624540.6071281371287976.53159912624495.607141349
1288034.03157952624407.2738325361288119.03155337624370.607174273
1288186.53153324624363.1071745151288219.86485579624330.607183195
1288224.03151959624276.4405324711288209.03152141624187.273892726
 1288241.5315058 623982.27395263 1288235.6981707623864.773987673
1288255.69816331623813.1073357841288254.86482804623738.940691161
1288290.69814817623649.7740499291288279.86481539623560.607410026

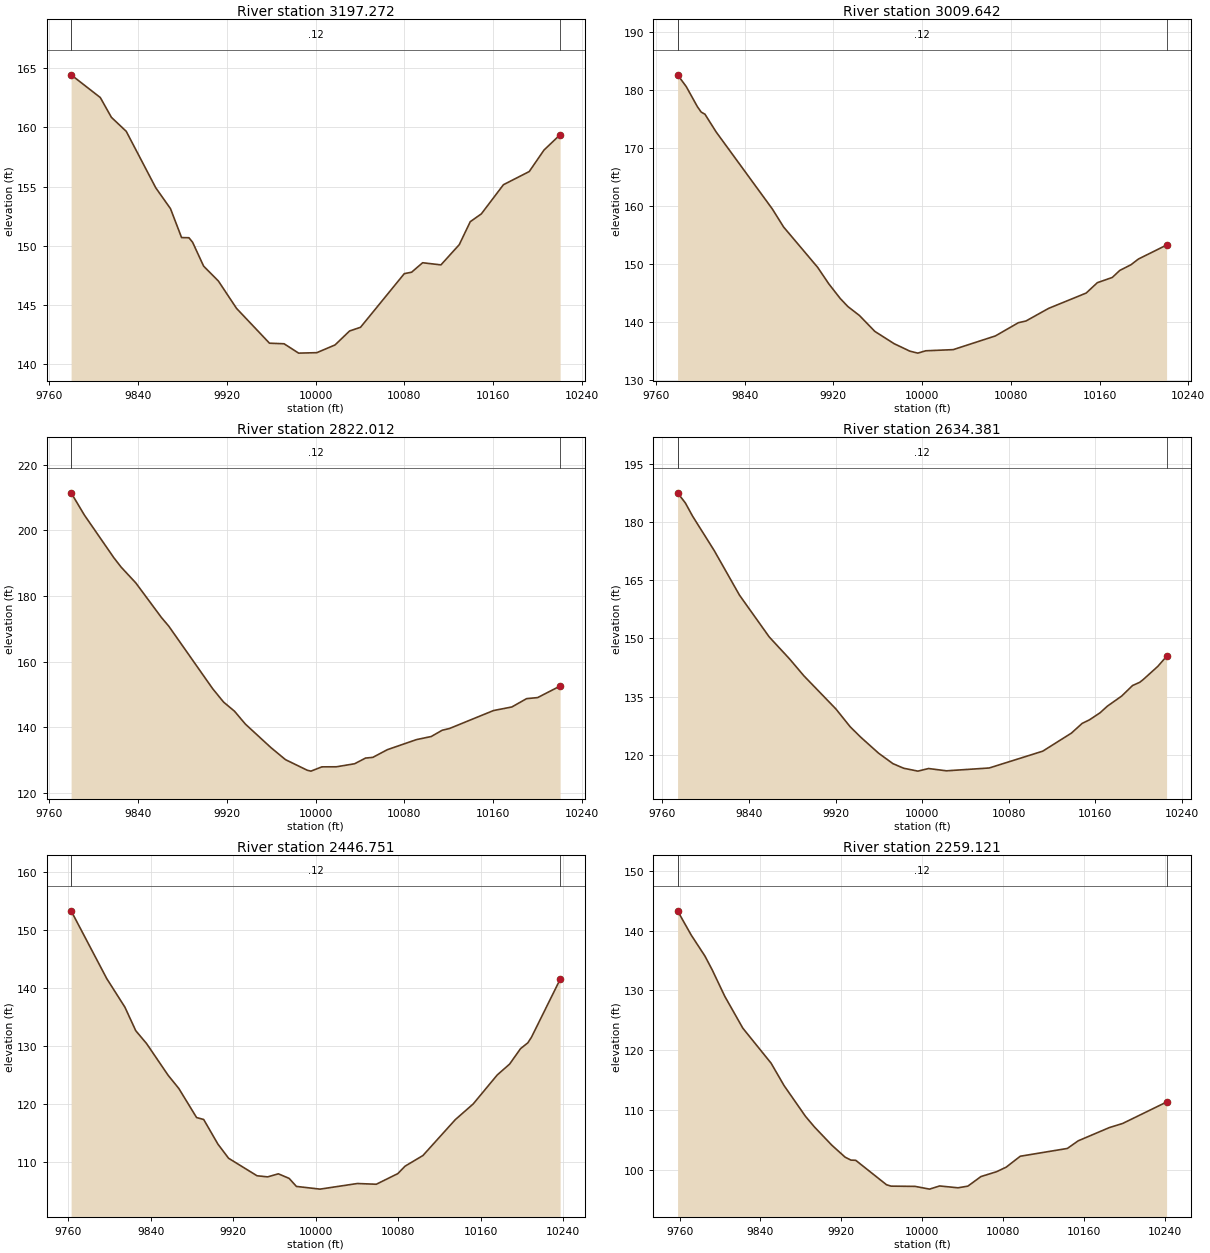
Type RM Length L Ch R = 1 ,3197.272,187.630300,187.630300,187.630300
XS GIS Cut Line= 6
1289143.16061571625465.6588438021289120.87164294625596.340119913
1289116.43974867625646.1646469651289111.45615127625763.678462401
1289104.43910493625822.4348183021289091.37636223625902.856606851
#Sta/Elev= 30
9779.545164.44269805.865162.52369815.887 160.8519829.249159.67039855.899154.8976
9869.169153.13799879.122150.70039885.757150.68549889.074 150.3059899.027148.2875
9912.296147.03399928.765 144.7139958.409141.7799 9971.55141.73329984.679140.9422
10001.09140.9812 10017.5 141.63310030.62142.812510040.48 143.12310079.95147.6539
10086.56147.775910096.47148.574910112.99148.393810129.51150.101610139.43152.0426
 10149.4   152.710169.34155.163210192.61156.2763 10205.9158.089110220.46159.3872
#Mann= 3 , 0 , 0
9779.545    0.12       09779.545    0.12       010220.46    0.12       0
#XS Ineff= 2 , 0
       0                               0
Bank Sta=9779.545,10220.46
Exp/Cntr=0.3,0.1

Type RM Length L Ch R = 1 ,3009.642,187.630300,187.630300,187.630300
XS GIS Cut Line= 6
1288999.82583649 625428.136086361288963.21784744 625571.57078114
1288947.51730768 625617.62158773 1288925.1693791625671.363895028
 1288907.0212993625727.7831057411288877.20672788625850.911393975
#Sta/Elev= 30
9779.549 182.5979787.366180.56839797.492177.07419800.867176.16089804.242175.7955
9814.368172.72349864.997159.43699875.147156.32739905.796149.37579916.013146.4851
9926.229143.98179933.137 142.5889943.536141.04779957.401138.30629974.732136.1907
9988.963134.89569996.101134.554310003.29134.958910028.04135.156210066.11137.5235
10086.79139.802910093.68140.103610114.03 142.27510147.94144.924710158.03146.7178
10171.49147.618210178.22148.827410188.32149.810810195.04150.798810220.44153.2106
#Mann= 3 , 0 , 0
9779.549    0.12       09779.549    0.12       010220.44    0.12       0
#XS Ineff= 2 , 0
       0                               0
Bank Sta=9779.549,10220.44
Exp/Cntr=0.3,0.1

Type RM Length L Ch R = 1 ,2822.012,187.630300,187.630300,187.630300
XS GIS Cut Line= 6
1288770.70230436625387.795146194 1288761.3914475625452.702720868
1288755.30901076625519.4453164761288754.30723567625648.794654626
1288751.87977576625694.3713172011288734.78905005625826.533568783
#Sta/Elev= 30
9779.545211.46329791.515204.67939818.031 191.684 9824.66  188.799837.917183.9558
9861.022173.40639867.611170.77459907.144151.7175 9917.01 147.6239926.859144.8337
9936.708140.88819959.688133.73739972.814130.05899992.501126.81749995.782126.5543
10005.63127.855810018.75127.877810035.15128.8035   10045130.537710051.57130.7525
10064.71133.103510091.01136.179610104.21137.111210114.11139.024110120.71  139.56
10160.36145.036310176.95146.129810190.22148.670710200.17148.990510220.46152.5158
#Mann= 3 , 0 , 0
9779.545    0.12       09779.545    0.12       010220.46    0.12       0
#XS Ineff= 2 , 0
       0                               0
Bank Sta=9779.545,10220.46
Exp/Cntr=0.3,0.1

Type RM Length L Ch R = 1 ,2634.381,187.630300,187.630300,187.630300
XS GIS Cut Line= 6
1288594.70772195625376.1211735391288584.82729753 625430.95387076
1288579.30632917  625472.68801531288556.65523837625711.662419847
1288548.14016092 625771.52043451 1288538.5348585625824.327796805
#Sta/Elev= 30
9774.002187.56539781.236184.93529787.903181.53689807.905172.6531 9831.23161.1609
9858.766150.36279877.535144.69749890.712140.35539920.358131.78669933.534127.2015
9943.417 124.4759959.887120.35939973.063117.67799982.946116.49599996.122115.7481
10006.01116.4198 10022.5115.827210062.06116.558810111.52120.897310138.03125.5591
10147.97128.0676 10154.6128.964910164.54130.808110171.17 132.494 10184.5135.1233
10194.51137.832610201.18138.670710204.51139.409410217.85 142.769   10226145.3681
#Mann= 3 , 0 , 0
9774.002    0.12       09774.002    0.12       0   10226    0.12       0
#XS Ineff= 2 , 0
       0                               0
Bank Sta=9774.002,10226
Exp/Cntr=0.3,0.1

Type RM Length L Ch R = 1 ,2446.751,187.630400,187.630400,187.630400
XS GIS Cut Line= 6
1288461.58338112625360.8447699291288432.08261618625437.504250964
1288393.47239109625557.660267697 1288372.5165995625608.302019358
1288330.70328367  625726.97355911288299.29597115625806.040976905
#Sta/Elev= 30
9762.982153.29559797.525141.60639815.102136.68719825.648132.61989836.194130.3889
9857.046124.92859867.385122.65849884.615117.64549891.507117.30929905.291113.0614
9915.629110.62469943.198107.60379953.536107.41279963.874107.93919974.295107.1557
9981.384105.765910004.28 105.29910040.44106.266110058.84106.140910079.71107.9761
10086.67109.251110104.06111.098210135.37 117.27410152.77119.991810175.99124.9755
10188.07126.865810198.66129.528210205.72130.528910209.25131.496210237.04141.4778
#Mann= 3 , 0 , 0
9762.982    0.12       09762.982    0.12       010237.04    0.12       0
#XS Ineff= 2 , 0
       0                               0
Bank Sta=9762.982,10237.04
Exp/Cntr=0.3,0.1

Type RM Length L Ch R = 1 ,2259.121,187.630300,187.630300,187.630300
XS GIS Cut Line= 6
1288387.66083147625310.2280545681288334.20231221625379.130239901
1288285.76584627 625436.280943041288252.18285585625471.298999033
1288161.81931031625557.7125692691288062.64556246625668.225013954
#Sta/Elev= 30
9757.911 143.3249771.424139.26669785.018135.75119792.186133.45069804.644129.0223
9822.483 123.6949850.507117.82639863.409114.0616 9884.55108.93059893.513107.1367
9910.716104.08629923.822102.09469929.548101.60429934.288101.57229964.734 97.4865
9969.312 97.24729993.07797.2076710007.3996.7478410017.3797.2788910035.5596.96898
10045.3297.2476910058.2798.8511510073.7799.6657710083.25100.4238 10097.2102.2525
10143.83103.555610154.51104.828410185.37 107.04610198.59107.737710242.07111.3245
#Mann= 3 , 0 , 0
9757.911    0.12       09757.911    0.12       010242.07    0.12       0
#XS Ineff= 2 , 0
       0                               0
Bank Sta=9757.911,10242.07
Exp/Cntr=0.3,0.1

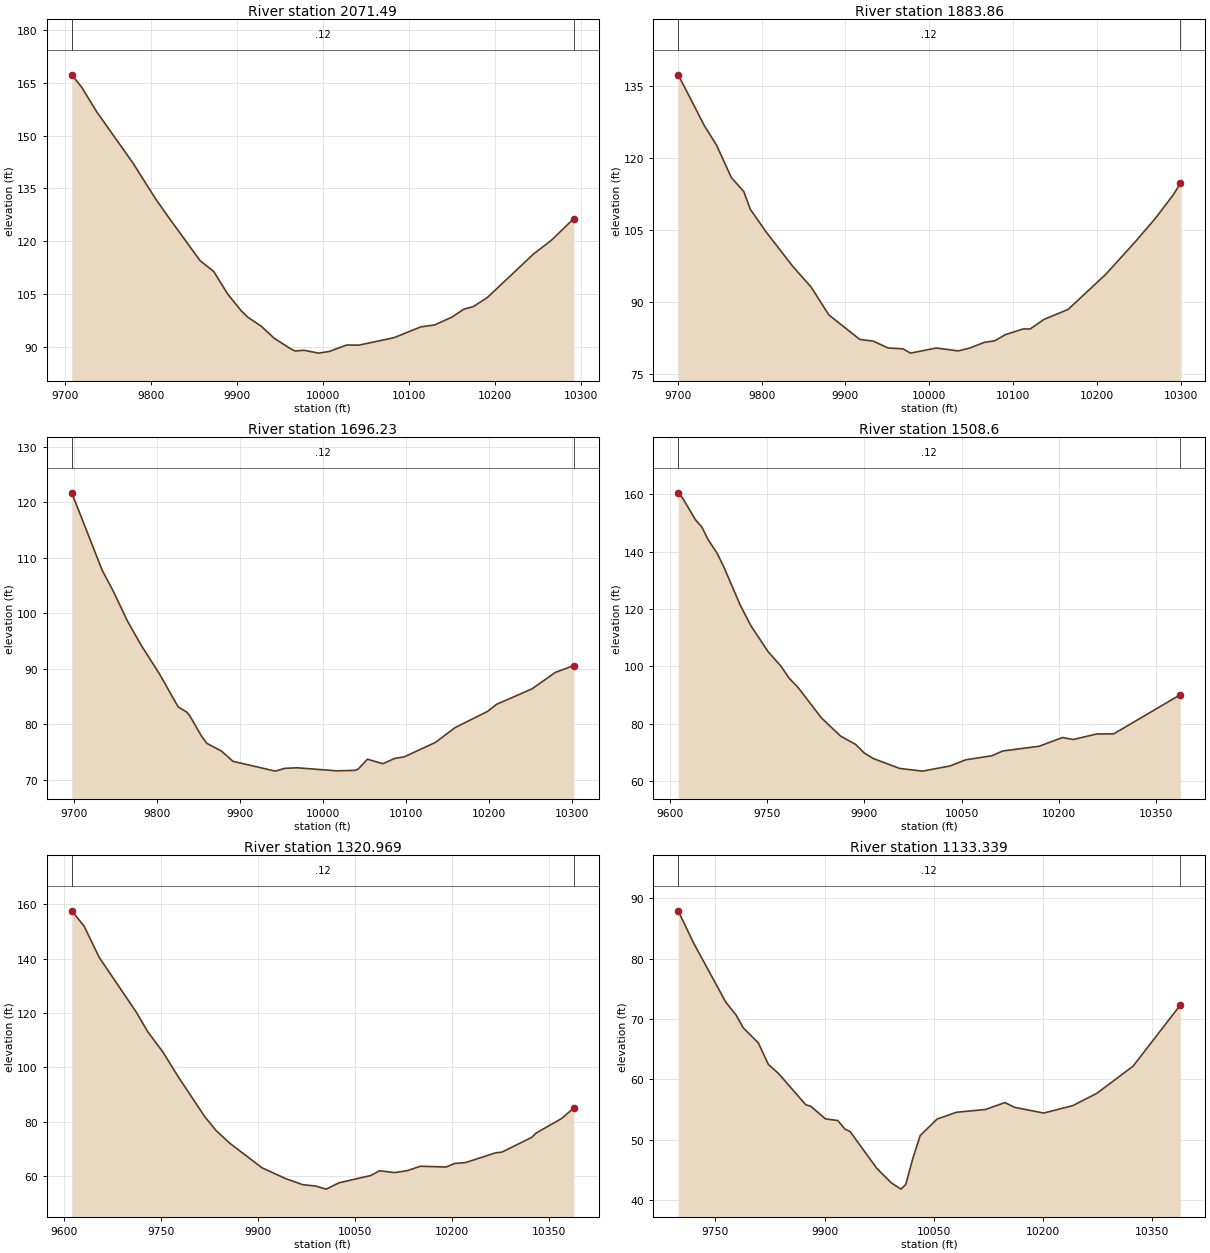
Type RM Length L Ch R = 1 , 2071.49,187.630300,187.630300,187.630300
XS GIS Cut Line= 6
1288353.68731303625174.2953140471288246.44940828 625259.81863817
1288135.29732538625332.9775530351288101.91706107625357.940020554
 1288013.3877051625416.5081020281287881.59132771625517.439143063
#Sta/Elev= 30
9707.932 167.3439719.479163.80069737.168156.73399778.982142.2897 9805.41132.0597
9820.379126.85219857.174114.46149873.121 111.3629889.114105.01919904.976100.2047
9912.74498.35722 9928.2895.804439943.39892.363749963.23789.247319967.91688.73607
9978.21388.93391 9995.1588.12324 10007.588.5970410027.6590.4276210041.9790.39989
10082.7292.5075610114.1995.6103210130.0796.1373910150.4498.4028610163.99100.6307
10175.05101.370510191.22 103.90410244.74 116.24710266.28120.316810292.07126.4446
#Mann= 3 , 0 , 0
9707.932    0.12       09707.932    0.12       010292.07    0.12       0
#XS Ineff= 2 , 0
       0                               0
Bank Sta=9707.932,10292.07
Exp/Cntr=0.3,0.1

Type RM Length L Ch R = 1 , 1883.86,187.630300,187.630300,187.630300
XS GIS Cut Line= 6
1288250.13384873625027.6741492891288185.16259084625061.241298456
1288113.46984156625107.5901891061288065.84452331625145.574937953
1287929.30657938625266.4877685271287769.35861608625381.442307977
#Sta/Elev= 30
9700.577137.39899731.861126.75219746.156122.77829763.896115.98399778.853113.0433
9786.515109.37459805.672104.5752 9837.21 97.45989859.209 93.11289880.25587.33473
9917.08782.234269933.22781.866739950.97280.443649968.716 80.26649977.58979.36836
10008.5880.4372710034.5479.8340610048.2180.4233410065.3681.5939210078.2381.95216
 10091.1 83.240410112.1384.4195710120.3684.4002210136.8186.39248 10165.688.48204
10210.3995.77199   10246102.640210269.94107.523310291.08 112.38610299.45114.7566
#Mann= 3 , 0 , 0
9700.577    0.12       09700.577    0.12       010299.45    0.12       0
#XS Ineff= 2 , 0
       0                               0
Bank Sta=9700.577,10299.45
Exp/Cntr=0.3,0.1

Type RM Length L Ch R = 1 , 1696.23,187.630400,187.630400,187.630400
XS GIS Cut Line= 6
1288170.27323835624953.773603534 1288058.4592069 624982.00699176
1287991.64137191625004.7005862661287951.67368169625022.662034454
1287786.93401582625108.176464183 1287612.3505093625182.287523716
#Sta/Elev= 30
9697.505121.67269734.067107.75069747.602103.93679764.52198.59391 9781.44 94.1436
9803.39689.002779825.731 83.09119836.12682.162489839.59181.53008 9853.4577.94355
 9860.3876.523949877.70575.163669891.87573.291749942.83671.529699954.06172.03159
9969.02872.1314910017.0371.5805510039.11 71.673110042.7971.9233210053.8373.68159
10072.2372.8671410086.96  73.831   1009874.0919910135.75 76.703910159.4179.37016
10198.7982.3100710209.4383.5714410251.9986.3412710280.3789.3267910302.5390.55311
#Mann= 3 , 0 , 0
9697.505    0.12       09697.505    0.12       010302.53    0.12       0
#XS Ineff= 2 , 0
       0                               0
Bank Sta=9697.505,10302.53
Exp/Cntr=0.3,0.1

Type RM Length L Ch R = 1 ,  1508.6,187.630300,187.630300,187.630300
XS GIS Cut Line= 6
1288256.39918564624904.1205573991288011.01103391624914.699769028
1287943.97414995624903.1058499581287837.61695211624862.760759237
1287761.73790788624846.507039843  1287494.146759624838.923920882
#Sta/Elev= 30
9613.219160.49629619.992 158.6759639.757151.10029649.639148.56639659.522144.0878
9672.699 139.5699682.581135.11019708.912121.24679725.346 114.078 9751.64105.1125
 9771.36100.08549784.48995.731639797.61392.673869833.72782.027439863.31775.65821
9886.47672.758069899.79769.76818 9913.2367.86987 9954.2364.378719989.46763.43062
 10032.165.2356510056.0867.3716510096.41 68.794810113.0770.4549810169.2272.10421
10205.3675.1482910221.7974.44947 10257.976.3866410284.1576.43395 10386.8 90.0776
#Mann= 3 , 0 , 0
9613.219    0.12       09613.219    0.12       0 10386.8    0.12       0
#XS Ineff= 2 , 0
       0                               0
Bank Sta=9613.219,10386.8
Exp/Cntr=0.3,0.1

Type RM Length L Ch R = 1 ,1320.969,187.630300,187.630300,187.630300
XS GIS Cut Line= 6
1288294.40506903624784.5008832331287996.52745404624706.272001005
1287951.46784463 624700.222037071287846.46011431624693.356648714
1287662.89455276624664.887108494 1287532.2710856624649.468812522
#Sta/Elev= 30
9611.965157.52979630.994151.9264 9654.61140.33849712.123120.15949729.199113.2053
9753.107105.56339777.01496.407149817.99881.773199835.07576.836849856.27972.15397
9906.07863.142569942.71459.163399969.16756.938519988.87656.44403 10005.355.31402
   1002557.6359610074.4560.3314410087.73 62.064410110.97  61.37910130.8962.12925
10150.81 63.718910190.6563.4389910203.9364.7512810220.5365.0548410266.9668.63797
10276.8768.9054110323.1274.3528110329.7375.9111210369.3881.2701510388.0785.14628
#Mann= 3 , 0 , 0
9611.965    0.12       09611.965    0.12       010388.07    0.12       0
#XS Ineff= 2 , 0
       0                               0
Bank Sta=9611.965,10388.07
Exp/Cntr=0.3,0.1

Type RM Length L Ch R = 1 ,1133.339,256.160500,256.160500,256.160500
XS GIS Cut Line= 6
1288262.75035909624600.0723981711288110.34761605624551.382326677
1288038.05859604624532.8599596921287909.05268642624512.510657281
1287715.60863271624477.3768236191287588.26434687624459.609915659
#Sta/Elev= 30
9698.81687.951889719.45382.727159764.22872.791299778.00570.725629788.33768.52685
9809.00366.032399822.77962.467099836.55660.987539874.18255.780539880.95655.54875
9901.27653.438639918.21153.167359928.371 51.7097 9935.1251.343339971.84545.23565
9991.738 42.836510004.9841.7846110011.6142.5362510021.5646.9317510031.51 50.6606
10054.7353.4059510081.3554.5322610121.3754.9971510148.0456.1385310161.3855.35533
10201.3954.4038410241.4155.6373610274.6657.6905410324.3562.1846910389.2572.32164
#Mann= 3 , 0 , 0
9698.816    0.12       09698.816    0.12       010389.25    0.12       0
#XS Ineff= 2 , 0
       0                               0
Bank Sta=9698.816,10389.25
Exp/Cntr=0.3,0.1

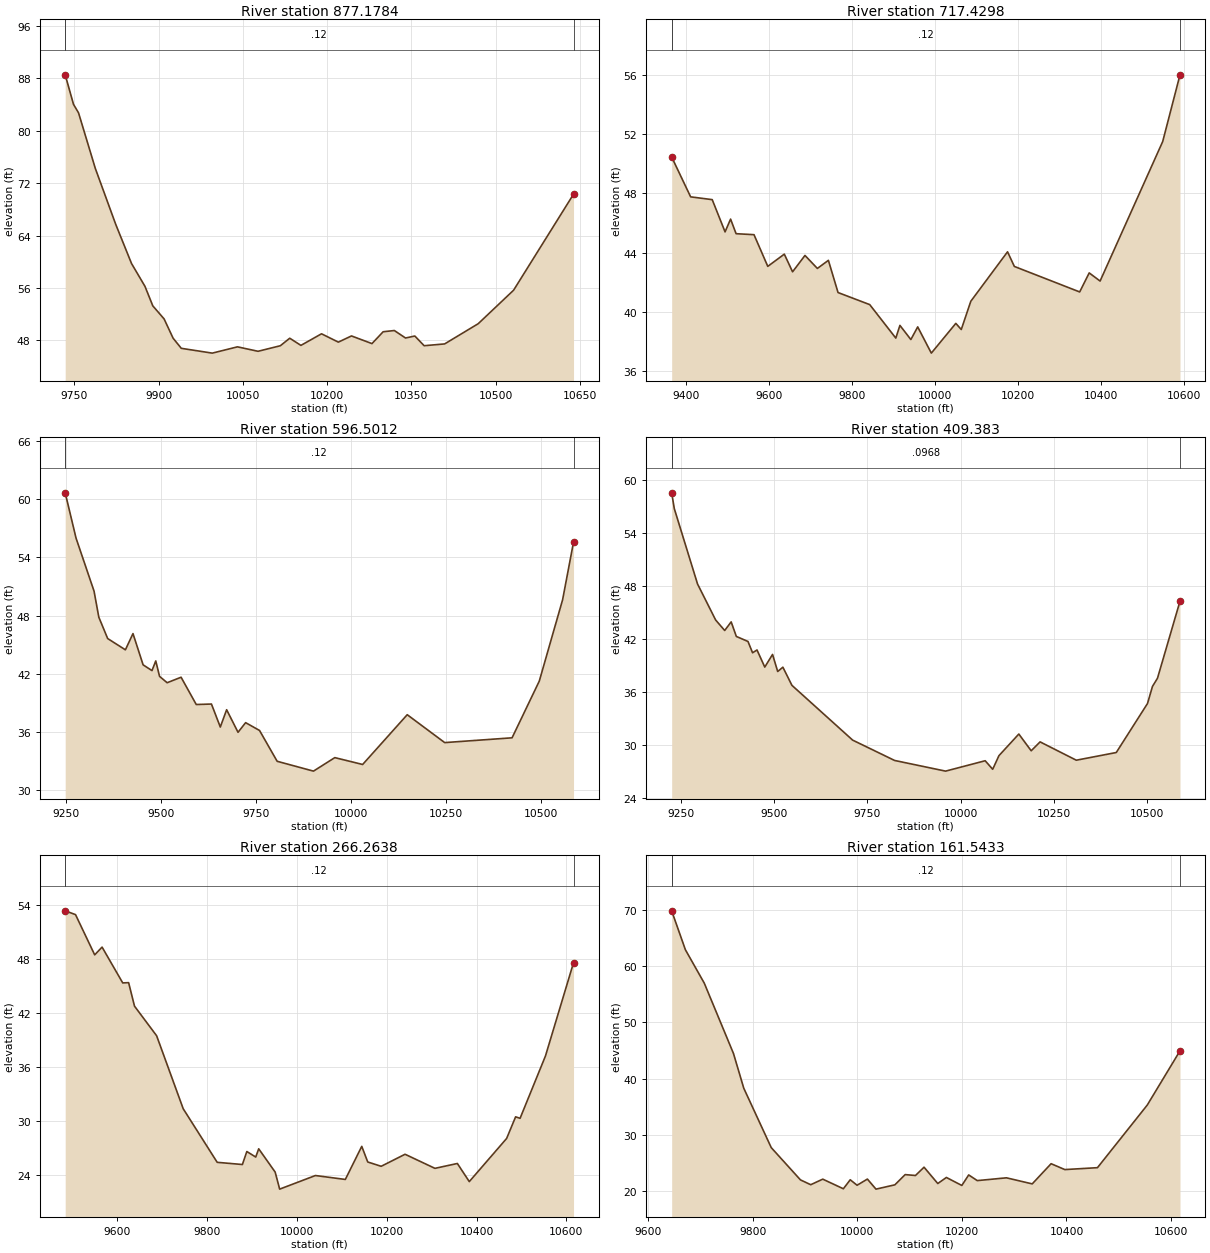
Type RM Length L Ch R = 1 ,877.1784,159.748600,159.748600,159.748600
XS GIS Cut Line= 6
1288301.64677125624578.3138915751288248.66906583624536.147892684
1288190.15395615624469.2789616581288129.87164548624316.198840708
1288076.15013844624309.4836523091287553.58069396624392.816985667
#Sta/Elev= 30
9733.52388.556349748.30684.048879757.28182.748239787.15674.263849823.39565.74786
9851.64559.74386 9875.5556.263449889.54753.276149909.62651.287049925.65748.34397
9940.253 46.79469995.46846.0603710040.3147.0196710076.9446.3410310116.6747.18778
10133.42 48.334710153.3447.24255   1019049.01171   1022047.7393810243.3448.68549
10279.8647.5154110299.77 49.321910319.6849.51209 10339.648.3688910356.1948.67226
10372.7847.1916310409.2947.4663510469.0350.5506110532.0855.6670410638.8370.33128
#Mann= 3 , 0 , 0
9733.523    0.12       09733.523    0.12       010638.83    0.12       0
#XS Ineff= 2 , 0
       09958.712        10037.04       0
Bank Sta=9733.523,10638.83
Exp/Cntr=0.3,0.1

Type RM Length L Ch R = 1 ,717.4298,120.928600,120.928600,120.928600
XS GIS Cut Line= 6
1288846.00690925624348.6546592561288340.62471721 624268.66368264
1288258.51979578 624260.021258981288223.74151155624258.650428295
1288189.20785001624259.6135871861287627.25690928624245.790075943
#Sta/Elev= 30
9365.37250.461919411.10847.76513 9463.1247.57715 9494.1545.395689507.43746.26045
9520.72345.273079563.90545.206859597.12243.062969636.98243.889679656.91242.69392
9686.80743.802129716.70242.922819743.276 43.47059766.52741.292399842.92640.47613
9905.83938.211019915.73639.069989942.12838.112529958.62338.968599991.46137.19449
10050.5439.2066810063.6738.7909610086.6440.7007410175.2544.0478610191.6643.05786
10349.1841.3332210372.1642.6203110398.4142.0693410549.3851.5067610591.0856.01962
#Mann= 3 , 0 , 0
9365.372    0.12       09365.372    0.12       010591.08    0.12       0
#XS Ineff= 2 , 0
       0  9884.7        10050.76       0
Bank Sta=9365.372,10591.08
Exp/Cntr=0.3,0.1

Type RM Length L Ch R = 1 ,596.5012,187.118200,187.118200,187.118200
XS GIS Cut Line= 6
 1288960.1562148624254.4706314951288434.11300012624163.346345261
1288283.42181018624149.7054774911288113.74093506  624119.7751984
1288051.25175714624105.1995673181287651.12843701623992.317853719
#Sta/Elev= 30
9248.57760.651469277.08555.988969324.50950.519059337.01947.842679360.32745.64221
9406.94344.482649426.92146.152389453.55942.934599476.86742.342569486.85643.33552
9496.84541.746229516.82341.09345 9553.4541.658589593.40638.847379633.362 38.8975
 9656.6736.529469673.318  38.3119703.28635.987549723.26436.979969759.89136.17519
 9806.2533.001539901.78331.987799957.91633.3781610031.1932.6721910148.4737.79901
10247.0734.9258510424.3335.4191910495.9241.2595710557.28 49.639410586.0255.57284
#Mann= 3 , 0 , 0
9248.577    0.12       09248.577    0.12       010586.02    0.12       0
#XS Ineff= 2 , 0
       09825.137         10082.3       0
Bank Sta=9248.577,10586.02
Exp/Cntr=0.3,0.1

Type RM Length L Ch R = 1 , 409.383,143.119200,143.119200,143.119200
XS GIS Cut Line= 6
 1288974.8046523624196.4194162041288519.94354123624041.905527309
 1288365.4296523623998.5027495471288276.88798565623965.516638428
1288140.31637472623936.3750431391287662.30465233623840.516638428
#Sta/Elev= 30
9225.56858.554519232.58956.768319294.95848.228729343.46844.155589367.72342.96809
9385.04743.944139398.90742.295039430.09241.727739442.38640.447649454.34740.76192
9475.13638.827469495.92640.256959509.78638.324099523.64638.81421  9547.9 36.7599
9710.67430.558069823.13228.255329959.78127.0470810065.9428.2225910086.07 27.2567
10102.8328.7980110156.1131.2448110189.29 29.350210213.1230.3578710310.2128.28352
10417.3329.1539210501.0234.7013310514.4136.64123 10527.837.5640910588.1446.28723
#Mann= 3 , 0 , 0
9225.568  0.0968       09225.568  0.0968       010588.14  0.0968       0
#XS Ineff= 2 , 0
       09831.812        10135.51       0
Bank Sta=9225.568,10588.14
Exp/Cntr=0.3,0.1

Type RM Length L Ch R = 1 ,266.2638,104.720500,104.720500,104.720500
XS GIS Cut Line= 6
1288764.73520789 623864.822193981288496.33198205623854.268015653
1288329.41148075623837.688078791 1288279.3414751623828.381891325
1288205.93229172623804.2155511531287646.67965233623712.044416219
#Sta/Elev= 30
9484.22353.303669507.19852.882119549.88148.411459566.29849.273849612.26545.29806
9625.39945.325159638.53242.714879687.78339.425099746.88431.323219822.60525.36912
9878.68225.125199888.59126.568519908.407 25.95429915.01326.870379951.66224.28342
9961.67322.3917210041.2523.9022310107.8723.4672710144.4427.1429310157.7425.40666
10187.6724.9279310240.8726.2633310307.3724.6992110357.2525.2400410383.8523.22841
10466.9828.0199610486.9330.42158 10496.930.2562410553.4337.18367 10615.947.54103
#Mann= 3 , 0 , 0
9484.223    0.12       09484.223    0.12       0 10615.9    0.12       0
#XS Ineff= 2 , 0
       0 9922.97        10121.09       0
Bank Sta=9484.223,10615.9
Exp/Cntr=0.3,0.1

Type RM Length L Ch R = 1 ,161.5433,117.726600,117.726600,117.726600
XS GIS Cut Line= 2
1288617.10065925623732.2484092711287645.74649262623686.675492615
#Sta/Elev= 30
9644.722 69.80349670.99262.89081 9707.12 56.95999762.956 44.47889782.66338.30952
9835.21427.766989891.04922.042639910.75621.183479933.74722.16951 9973.1620.46295
9986.29822.059439999.43621.0892910019.1422.1809810035.5620.3994310071.6921.16154
 10091.422.9763710111.1122.8197310127.5324.29128 10153.821.3924110170.2322.47006
10199.7921.0517310212.9222.9167710229.3521.9121210285.1822.4069610334.4521.32943
10370.5824.9115110396.8523.8694210459.2624.2078410554.5135.3204810617.15 44.9458
#Mann= 3 , 0 , 0
9644.722    0.12       09644.722    0.12       010617.15    0.12       0
#XS Ineff= 2 , 0
       09935.445        10092.54       0
Bank Sta=9644.722,10617.15
Exp/Cntr=0.3,0.1

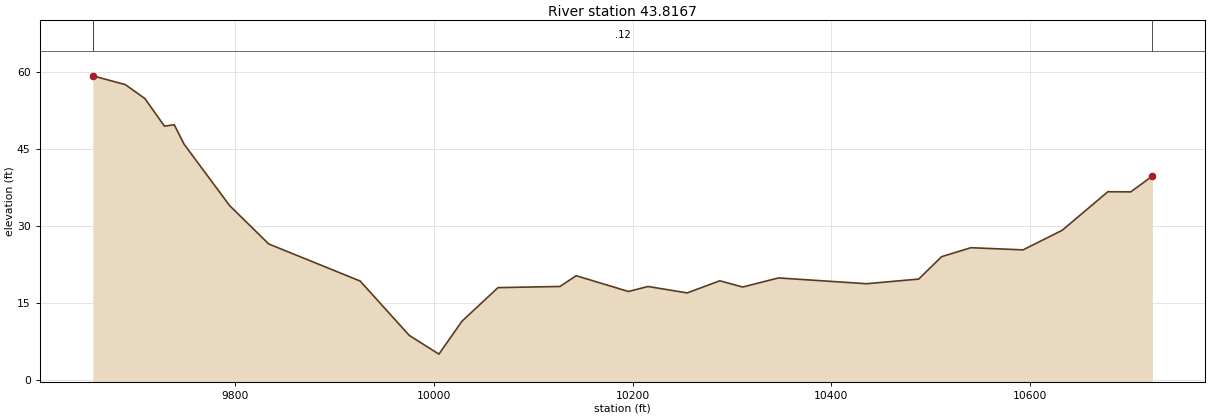
Type RM Length L Ch R = 1 , 43.8167,0.000000,0.000000,0.000000
XS GIS Cut Line= 6
1288630.18659675  623585.30830511288407.11983535623592.937080503
1288334.41850868623598.1104595511288238.90838555 623611.50229235
 1288183.9468241623613.8606354741287565.08243009  623585.3083051
#Sta/Elev= 30
 9656.4559.157849689.24557.446179708.94954.730359728.65249.358669738.50349.63416
9748.35545.861519794.32133.879549833.70126.415439925.69319.204079975.1988.615393
10005.02 4.9719510028.2111.3677710064.5117.9190910126.8918.14437 10143.320.23937
10195.8817.1663710215.6218.1407410255.08 16.892410287.9219.2524910310.9118.03482
10347.0319.80882 10435.718.6781210488.2419.5874710511.2323.9454910540.79 25.6939
10593.3325.2707210632.7429.0913210678.7136.59269 10701.7 36.556810723.5639.65156
#Mann= 3 , 0 , 0
 9656.45    0.12       0 9656.45    0.12       010723.56    0.12       0
#XS Ineff= 2 , 0
       09942.408        10073.19       0
Bank Sta=9656.45,10723.56
Exp/Cntr=0.3,0.1